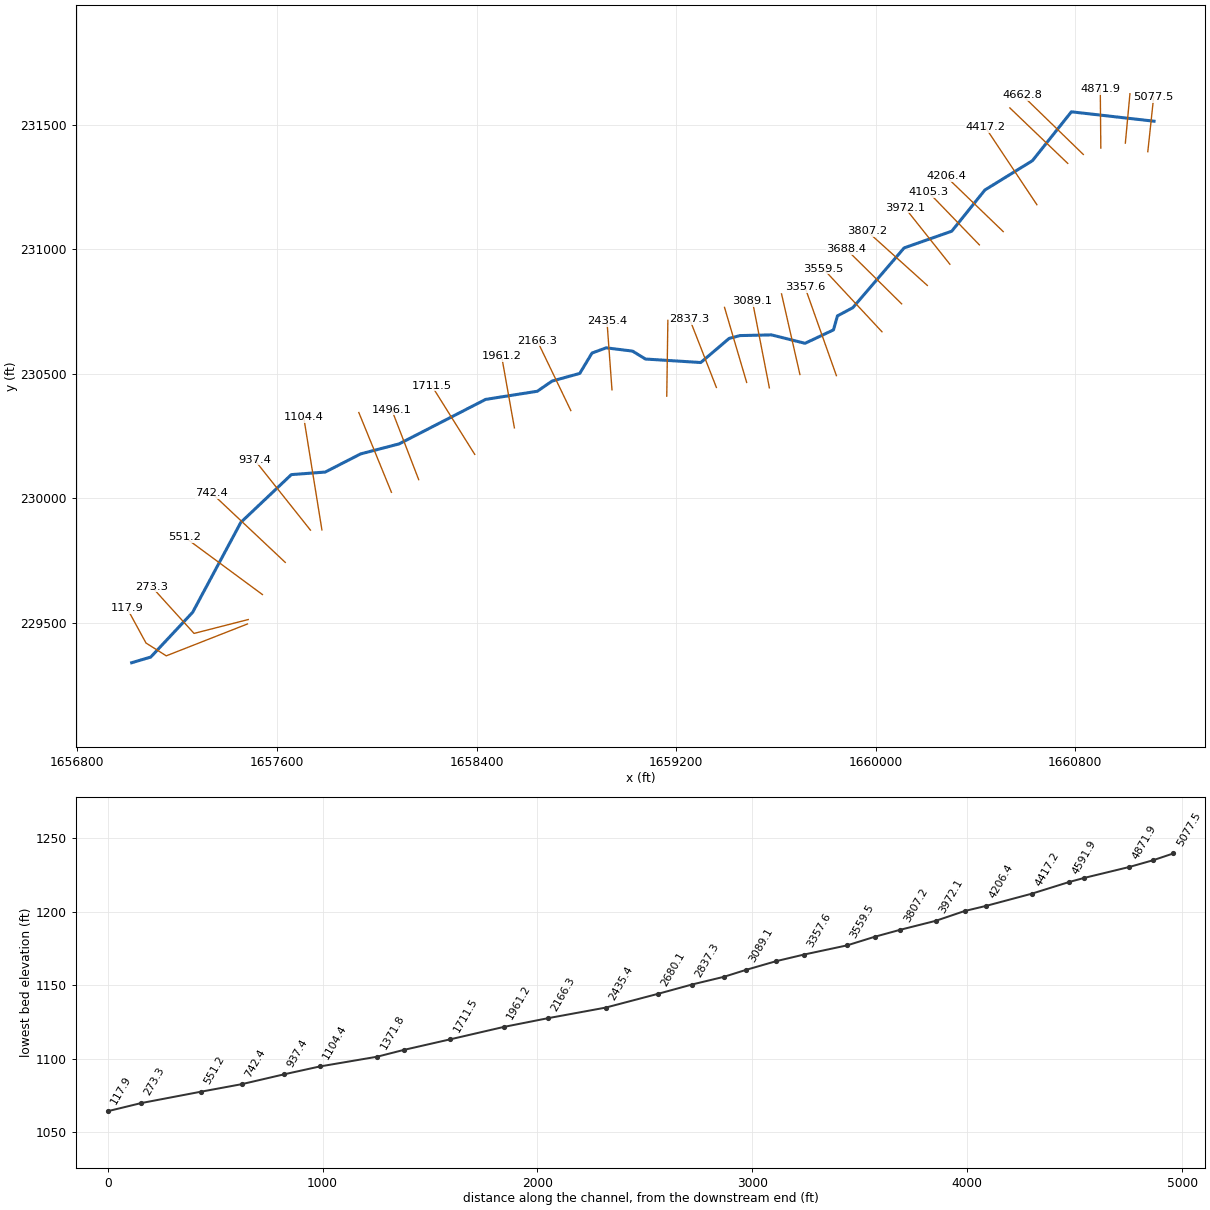
--- strghtfrk.prj (project) ---

Proj Title=strghtfrk
Current Plan=p01
Default Exp/Contr=0,0
English Units
Geom File=g01
Flow File=f01
Plan File=p01
BEGIN DESCRIPTION:
END DESCRIPTION:
DSS Export Rating Curves= 0
DSS Export Rating Curve Sorted= 0
DSS Export Volume Flow Curves= 0
DXF OffsetX= 0
DXF OffsetY= 0
DXF ScaleX= 0
DXF ScaleY= 0

--- strghtfrk.p01 (plan) ---

Plan Title=Approximate Study - 100yr
Program Version=4.00
Geom File=g01
Flow File=f01
Subcritical Flow
K Sum by GR= 0
Std Step Tol= 0.01
Critical Tol= 0.01
Num of Std Step Trials= 20
Max Error Tol= 0.3
Flow Tol Ratio= 0.001
Split Flow NTrial= 30
Split Flow Tol= 0.02
Split Flow Ratio= 0.02
Log Output Level= 0
Friction Slope Method= 1
Unsteady Friction Slope Method= 2
Unsteady Bridges Friction Slope Method= 1
Parabolic Critical Depth
Global Vel Dist= 0 , 0 , 0
Global Log Level= 0
CheckData=True
Encroach Param=-1 ,0,0, 0
Run HTab= 0
Run UNet= 0
Run PostProcess= 0
Run WQNet= 0
UNET Theta= 0
UNET Theta Warmup= 0
UNET ZTol= 0
UNET ZSATol= 0
UNET MxIter= 0
UNET MaxInSteps= 0
UNET DtIC= 0
UNET DtMin= 0
UNET MaxCRTS= 0
UNET WFStab= 0
UNET SFStab= 0
UNET WFX= 1
UNET SFX= 1
UNET DSS MLevel= 1
UNET DZMax Abort= 0
UNET Convert EG Bridges= 0
UNET Use Existing IB Tables= 0
UNET Froude Reduction=False
UNET Froude Limit= 0
UNET Froude Power= 0
UNET Time Slicing=0,0, 5
Write IC File= 0
Echo Input=False
Echo Output=False
Write Detailed= 0
Detailed Automatic Start=False, 0
WQ ULTIMATE=-1
WQ Max Comp Step=1HOUR
WQ Output Interval=15MIN
WQ Output Selected Increments= 0
WQ Output face flow=0
WQ Output face velocity=0
WQ Output face area=0
WQ Output face dispersion=0
WQ Output cell volume=0
WQ Output cell surface area=0
WQ Output cell continuity=0
WQ Output face conc=0
WQ Output face dconc_dx=0
WQ Output face courant=0
WQ Output face peclet=0
WQ Output face adv mass=0
WQ Output face disp mass=0
WQ Output cell mass=0
WQ Output cell source sink temp=0
WQ Output cell source sink nsm=0
WQ Output MaxMinRange=-1
WQ Daily Max Min Mean=-1
WQ Daily Range=0
WQ Daily Time=0
WQ Create Restart=0
WQ Fixed Restart=0
WQ System Summary=False
Sorting and Armoring Iterations= 10
XS Update Threshold= 0.02
Hydraulics Update Threshold= 0.02
Energy Slope Method= 1
Volume Change Method= 0
XS Weighting Method= 0
Number of US Weighted Cross Sections= 1
Number of DS Weighted Cross Sections= 1
Upstream XS Weight=0.25
Main XS Weight=0.5
Downstream XS Weight=0.25
Number of DS XS's Weighted with US Boundary= 1
Upstream Boundary Weight= 1
Weight of XSs Associated with US Boundary= 0
Number of US XS's Weighted with DS Boundary= 1
Downstream Boundary Weight= 0.5
Weight of XSs Associated with DS Boundary= 0.5
Sediment Output Level= 4
Mass or Volume Output= 0
Output Increment Type= 1
Profile and TS Output Increment= 10
XS Output Flag= 0
XS Output Increment= 10
Disregard all LS=0
Disregard all Conn=0
Disregard all Breaches=0
Disregard all Pumps=0

--- strghtfrk.f01 (steady flow) ---

Flow Title=USGS Regression Equation
Program Version=4.00
Number of Profiles= 1
Profile Names=P100yr
River Rch & RM=strghtfrk,Main            ,5077.5
     331
River Rch & RM=strghtfrk,Main            ,4662.8
     358
River Rch & RM=strghtfrk,Main            ,3559.5
     392
River Rch & RM=strghtfrk,Main            ,1711.5
     425
River Rch & RM=strghtfrk,Main            ,1496.1
     522
River Rch & RM=strghtfrk,Main            ,551.2
     533
River Rch & RM=strghtfrk,Main            ,273.3
     771
Boundary for River Rch & Prof#=strghtfrk,Main            , 1
Up Type= 0
Dn Type= 3
Dn Slope=0.016138
DSS Import GetInterval= 0
DSS Import GetPeak= 0
DSS Import FillOption= 0

--- strghtfrk.g01 (geometry) ---

Geom Title=USGS 3m DEM
Program Version=4.00

River Reach=strghtfrk       ,Main
Reach XY= 30
     1661115.515      231513.894     1660784.107      231551.633
     1660628.001       231355.33     1660437.496      231237.561
     1660304.607      231072.127     1660113.807      231005.032
     1659908.152      230764.921      1659846.55      230731.994
     1659830.609       230675.71     1659716.816      230621.955
     1659582.182      230655.737      1659455.77      230652.919
     1659412.525      230641.513     1659298.818      230544.722
     1659077.146      230558.754     1659025.078       230590.67
     1658919.677      230603.728     1658862.871      230582.713
     1658813.813      230500.989     1658703.004      230470.341
     1658643.637      230429.332     1658436.524      230396.622
     1658089.395      230217.803     1657935.749      230177.825
     1657793.761       230104.87     1657657.743      230094.541
     1657455.433      229902.698     1657262.227      229541.471
     1657094.379      229361.807     1657017.878      229338.995

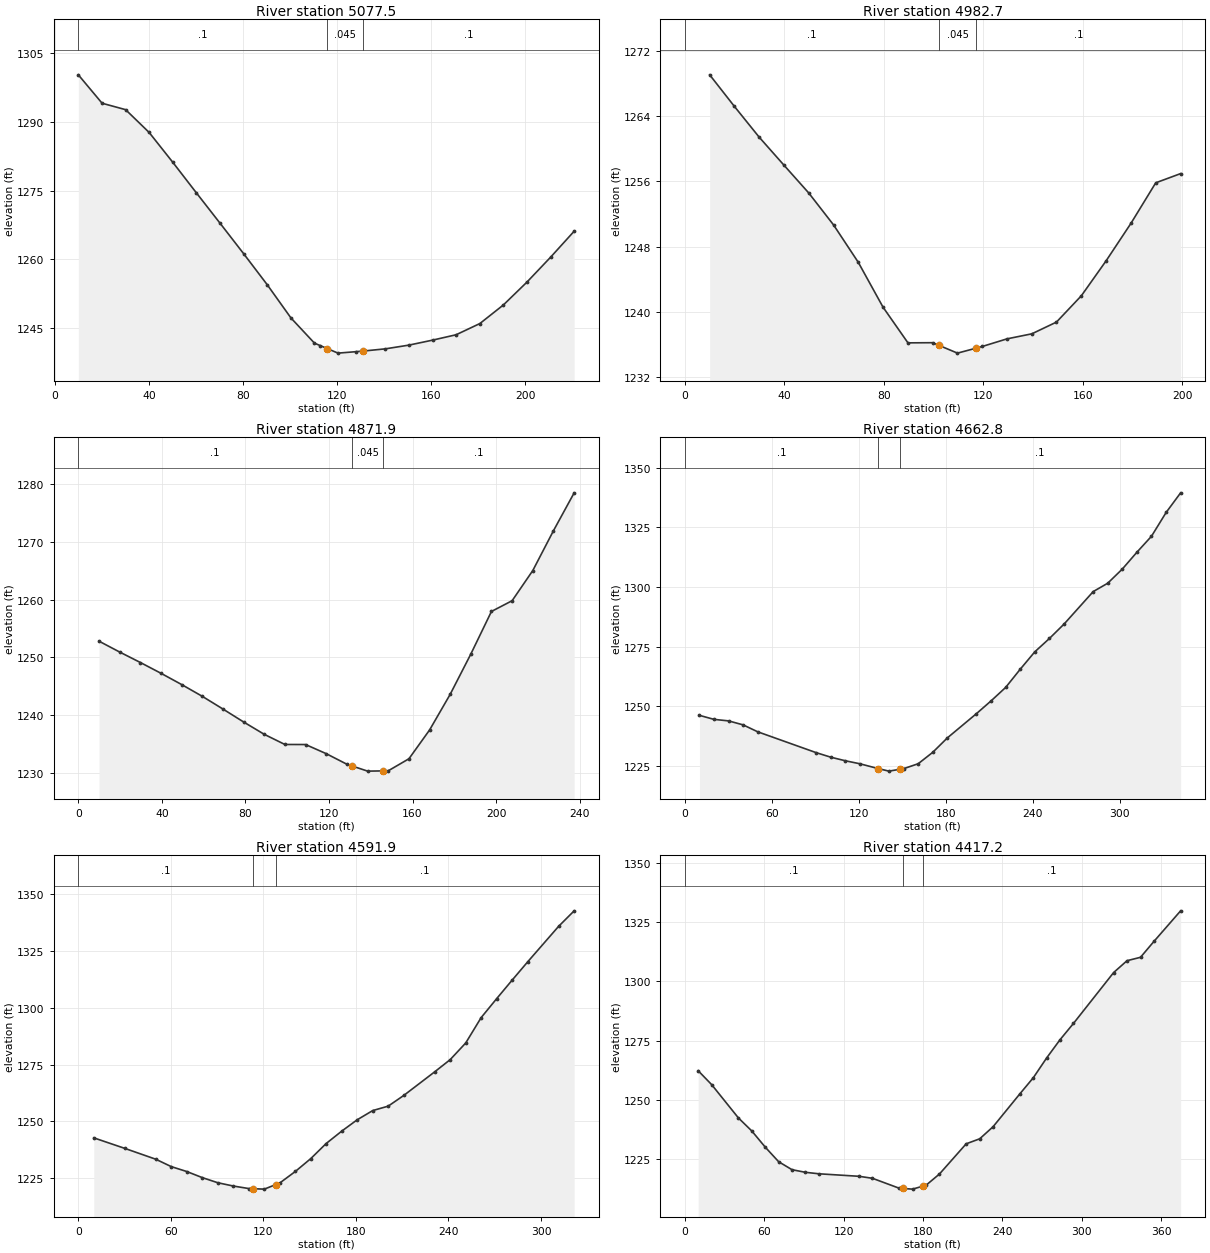
Type RM Length L Ch R = 1 ,5077.5  ,94.5,94.8,95.1
XS GIS Cut Line= 2
     1661090.488       231391.52     1661113.892      231611.071
#Sta/Elev= 26
      10 1300.21    20.1 1294.02    30.1 1292.62    40.1 1287.66    50.2 1281.13
    60.2 1274.49    70.3 1267.85    80.3 1261.23    90.3 1254.49   100.4 1247.24
   110.4 1241.75   112.9 1241.21   115.91240.558   120.4 1239.58   127.9 1239.89
   130.5    1240   130.9 1240.02   140.5 1240.51   150.5 1241.32   160.6 1242.41
   170.6 1243.58   180.7 1246.02   190.7 1250.07   200.7 1255.04   210.8 1260.49
   220.8 1266.14
#Mann= 3 , 0 , 0
      10      .1       0   115.9    .045       0   130.9      .1       0
Bank Sta=115.9,130.9
XS Rating Curve= 0 ,0
Exp/Cntr=0.3,0.1

Type RM Length L Ch R = 1 ,4982.7  ,108.5,110.8,113.1
XS GIS Cut Line= 2
     1661000.421      231425.799     1661018.838      231624.199
#Sta/Elev= 22
      10 1269.08    19.9 1265.22    29.9 1261.43    39.9 1257.98    49.8 1254.59
    59.8 1250.66    69.7 1246.09    79.7 1240.56    89.7 1236.19    99.6 1236.21
   102.1 1235.89   109.6 1234.93   117.1 1235.54   119.6 1235.75   129.5 1236.68
   139.5  1237.3   149.4 1238.74   159.4 1241.97   169.4 1246.28   179.3 1250.84
   189.3 1255.83   199.3 1256.96
#Mann= 3 , 0 , 0
       0      .1       0   102.1    .045       0   117.1      .1       0
Bank Sta=102.1,117.1
XS Rating Curve= 0 ,0
Exp/Cntr=0.3,0.1

Type RM Length L Ch R = 1 ,4871.9  ,191.2,209.1,227
XS GIS Cut Line= 2
     1660902.142      231406.008     1660899.913       231643.39
#Sta/Elev= 26
     9.9 1252.82    19.8 1250.94    29.7 1249.13    39.6 1247.26    49.5 1245.31
    59.3 1243.29    69.2 1241.09    79.1 1238.85      89 1236.71    98.9 1234.95
   108.8 1234.94   118.7 1233.36   128.6 1231.53     131 1231.24   138.5 1230.34
     146 1230.38   148.4  1230.4   158.3 1232.48   168.2 1237.47     178  1243.6
   187.9 1250.57   197.8 1257.96   207.7 1259.82   217.6 1265.04   227.5 1271.93
   237.4 1278.48
#Mann= 3 , 0 , 0
       0      .1       0     131    .045       0     146      .1       0
Bank Sta=131,146
XS Rating Curve= 0 ,0
Exp/Cntr=0.3,0.1

Type RM Length L Ch R = 1 ,4662.8  ,70.8,70.9,71.1
XS GIS Cut Line= 2
     1660831.931      231380.375     1660586.747      231618.872
#Sta/Elev= 30
    10.1 1246.28    20.1  1244.6    30.2 1243.96    40.2  1242.3    50.3 1239.39
    90.5 1230.69   100.6 1228.78   110.7 1227.27   120.7 1226.02   133.3 1224.01
   140.8 1222.93   148.3 1223.69   150.9 1223.95     161 1226.03     171 1230.79
   181.1 1236.84   201.2 1247.01   211.3 1252.36   221.3 1257.96   231.4 1265.61
   241.4 1272.86   251.5 1278.46   261.6 1284.49   281.7 1298.09   291.7 1301.58
   301.8 1307.53   311.9  1314.6   321.9 1321.25     332 1331.21     342 1339.43
#Mann= 3 , 0 , 0
       0      .1       0   133.3    .045       0   148.3      .1       0
Bank Sta=133.3,148.3
XS Rating Curve= 0 ,0
Exp/Cntr=0.3,0.1

Type RM Length L Ch R = 1 ,4591.9  ,179.6,174.7,169.8
XS GIS Cut Line= 2
     1660769.372      231344.597     1660537.486      231567.274
#Sta/Elev= 30
      10 1242.72    30.1 1238.08    50.2  1233.3    60.3 1230.03    70.3 1227.88
    80.4 1225.19    90.4 1222.94   100.5 1221.48   110.5 1220.38   113.1 1220.31
   120.6 1220.12   128.1 1222.14   130.6 1222.81   140.7  1227.9   150.7 1233.56
   160.7 1240.22   170.8 1245.68   180.8 1250.67   190.9 1254.74   200.9 1256.68
     211 1261.39   231.1 1271.82   241.1 1277.17   251.2 1284.53   261.2 1295.71
   271.3 1304.09   281.3 1312.22   291.4  1320.3   311.4  1335.9   321.5 1342.75
#Mann= 3 , 0 , 0
       0      .1       0   113.1    .045       0   128.1      .1       0
Bank Sta=113.1,128.1
XS Rating Curve= 0 ,0
Exp/Cntr=0.3,0.1

Type RM Length L Ch R = 1 ,4417.2  ,205.9,210.7,215.6
XS GIS Cut Line= 2
     1660645.814      231178.656     1660438.522      231490.708
#Sta/Elev= 30
    10.1 1262.24    20.3 1256.35    40.5 1242.27    50.6 1236.76    60.8 1229.89
    70.9 1223.74      81 1220.36    91.1 1219.26   101.3 1218.63   131.6 1217.57
   141.8 1216.72     162 1212.52   164.6 1212.42   172.1 1212.14   179.6 1213.36
   182.3  1213.8   192.4 1218.54   212.6 1231.32   222.8 1233.43   232.9 1238.54
   253.1 1252.42   263.3 1259.27   273.4 1267.66   283.5 1275.36   293.6 1282.22
     324 1303.78   334.1 1308.79   344.3 1310.23   354.4 1316.92   374.6 1329.89
#Mann= 3 , 0 , 0
       0      .1       0   164.6    .045       0   179.6      .1       0
Bank Sta=164.6,179.6
XS Rating Curve= 0 ,0
Exp/Cntr=0.3,0.1

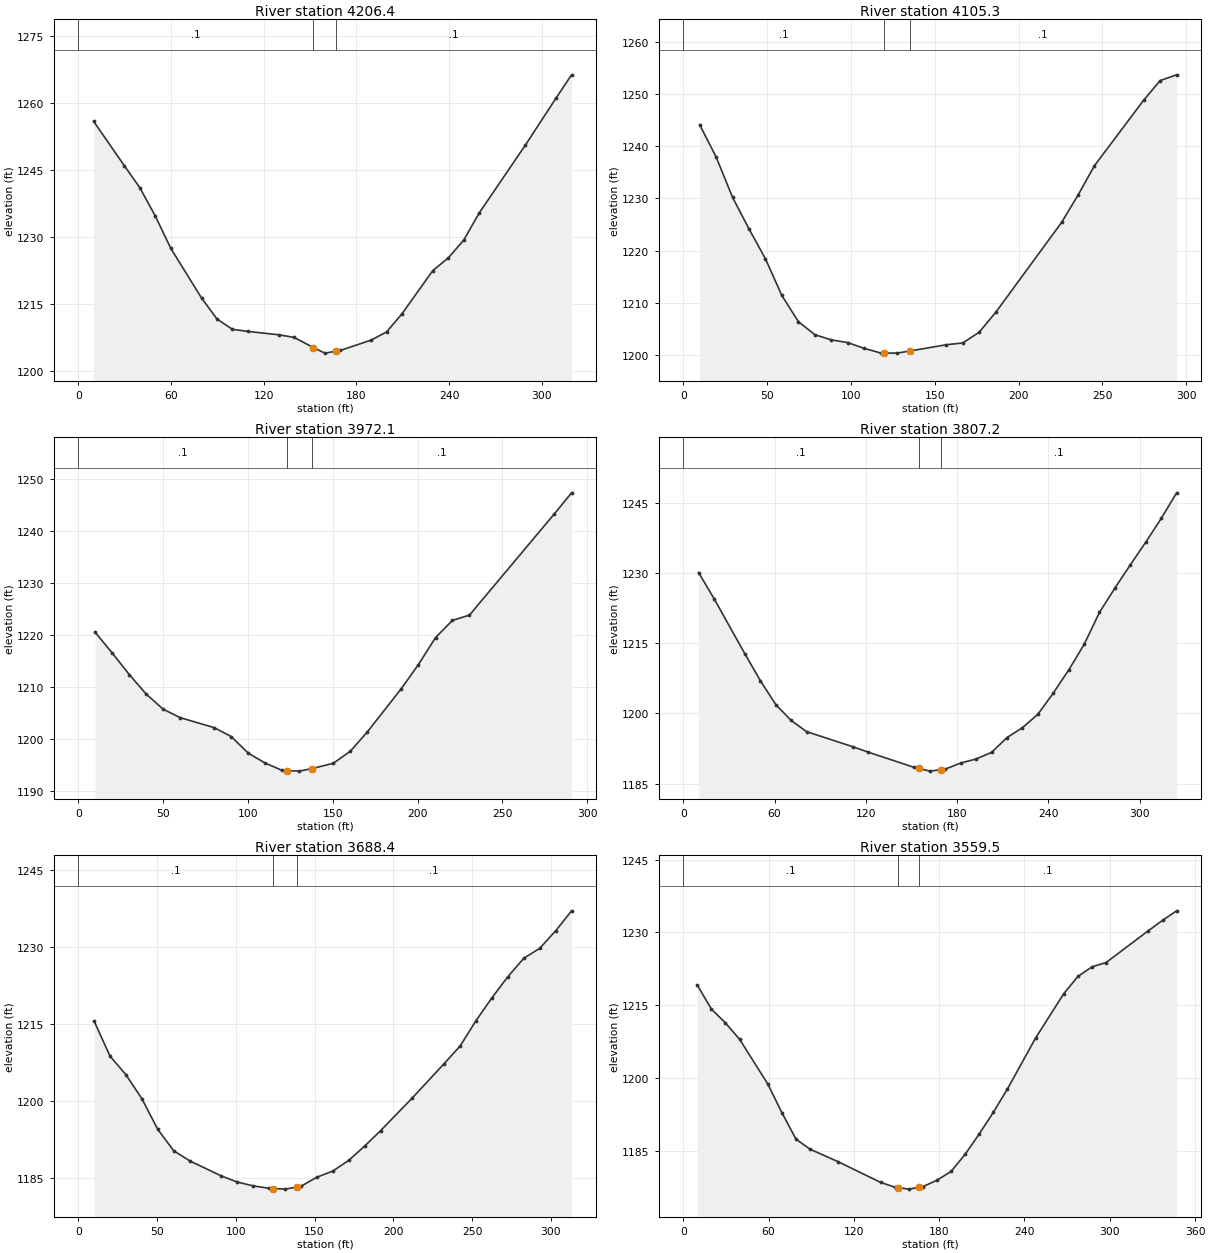
Type RM Length L Ch R = 1 ,4206.4  ,102,101.2,100.3
XS GIS Cut Line= 2
     1660510.963      231070.552     1660281.382      231292.332
#Sta/Elev= 25
      10 1255.78    29.9 1245.83    39.9 1240.92    49.9 1234.58    59.9 1227.36
    79.8 1216.25    89.8 1211.54    99.8 1209.24   109.7 1208.77   129.7 1208.02
   139.7 1207.43   152.1 1205.16   159.6 1203.91   167.1 1204.36   169.6 1204.51
   189.5 1206.82   199.5 1208.65   209.5 1212.72   229.4 1222.38   239.4 1225.21
   249.4 1229.19   259.4 1235.26   289.3 1250.46   309.2 1261.02   319.2  1266.2
#Mann= 3 , 0 , 0
       0      .1       0   152.1    .045       0   167.1      .1       0
Bank Sta=152.1,167.1
XS Rating Curve= 0 ,0
Exp/Cntr=0.3,0.1

Type RM Length L Ch R = 1 ,4105.3  ,135.1,133.2,131.2
XS GIS Cut Line= 2
     1660415.264      231017.278     1660211.004      231229.072
#Sta/Elev= 25
     9.8 1244.12    19.6 1237.95    29.4 1230.22    39.2 1224.17      49 1218.45
    58.8 1211.41    68.7 1206.39    78.5  1203.9    88.3 1202.91    98.1 1202.39
   107.9 1201.28   117.7  1200.4     120 1200.39   127.5 1200.37     135 1200.77
   156.9 1201.98   166.7 1202.32   176.5 1204.38   186.4 1208.21   225.6  1225.4
   235.4 1230.63   245.2 1236.27   274.6 1248.84   284.4 1252.58   294.2 1253.68
#Mann= 3 , 0 , 0
       0      .1       0     120    .045       0     135      .1       0
Bank Sta=120,135
XS Rating Curve= 0 ,0
Exp/Cntr=0.3,0.1

Type RM Length L Ch R = 1 ,3972.1  ,161.4,164.9,168.4
XS GIS Cut Line= 2
     1660297.229      230939.424     1660116.408      231167.124
#Sta/Elev= 24
      10 1220.48    20.1 1216.48    30.1 1212.35    40.1 1208.58    50.1 1205.67
    60.2 1204.04    80.2 1202.12    90.2 1200.41   100.3 1197.19   110.3 1195.29
   120.3 1193.88   122.8 1193.85   130.3 1193.75   137.8 1194.23   150.4 1195.27
   160.4 1197.58   170.4 1201.29   190.5 1209.66   200.5 1214.25   210.6 1219.46
   220.6 1222.78   230.6 1223.79   280.7 1243.31   290.8 1247.34
#Mann= 3 , 0 , 0
       0      .1       0   122.8    .045       0   137.8      .1       0
Bank Sta=122.8,137.8
XS Rating Curve= 0 ,0
Exp/Cntr=0.3,0.1

Type RM Length L Ch R = 1 ,3807.2  ,119.8,118.9,117.9
XS GIS Cut Line= 2
     1660206.713      230854.345     1659965.987      231071.667
#Sta/Elev= 29
    10.1 1230.07    20.3 1224.49    40.5 1212.74    50.7 1206.98    60.8  1201.9
    70.9  1198.5    81.1  1196.1   111.5 1192.88   121.6 1191.72     152 1188.45
   154.7 1188.24   162.2 1187.67   169.7    1188   172.3 1188.11   182.4  1189.4
   192.6 1190.27   202.7 1191.68   212.8 1194.83     223 1196.95   233.1 1199.81
   243.2 1204.32   253.4 1209.28   263.5 1214.72   273.6 1221.57   283.8  1226.8
   293.9 1231.74     304 1236.56   314.2 1241.64   324.3 1247.11
#Mann= 3 , 0 , 0
       0      .1       0   154.7    .045       0   169.7      .1       0
Bank Sta=154.7,169.7
XS Rating Curve= 0 ,0
Exp/Cntr=0.3,0.1

Type RM Length L Ch R = 1 ,3688.4  ,129.8,128.9,127.9
XS GIS Cut Line= 2
     1660103.851      230780.369     1659881.173      231000.535
#Sta/Elev= 30
    10.1 1215.65    20.2 1208.81    30.3  1205.2    40.4 1200.52    50.5 1194.55
    60.6 1190.39    70.7 1188.43    90.9 1185.47     101 1184.29   111.1 1183.54
   121.2 1183.07   123.8 1183.03   131.3 1182.91   138.8 1183.32   141.4 1183.47
   151.5 1185.24   161.6 1186.43   171.7 1188.51   181.8  1191.3   191.9  1194.3
   212.1  1200.7   232.3 1207.38   242.4  1210.8   252.5 1215.76   262.6  1220.2
   272.7 1224.31   282.8 1227.89   292.9 1229.83     303 1233.23   313.1 1237.13
#Mann= 3 , 0 , 0
       0      .1       0   123.8    .045       0   138.8      .1       0
Bank Sta=123.8,138.8
XS Rating Curve= 0 ,0
Exp/Cntr=0.3,0.1

Type RM Length L Ch R = 1 ,3559.5  ,211.1,201.9,192.7
XS GIS Cut Line= 2
     1660025.054      230668.229     1659788.786      230922.328
#Sta/Elev= 29
     9.9  1219.1    19.8 1214.18    29.7 1211.31    39.7 1207.92    59.5 1198.71
    69.4  1192.8    79.3 1187.36    89.2 1185.28     109  1182.7   138.8 1178.44
   148.7 1177.46   151.1 1177.36   158.6 1177.05   166.1 1177.43   168.5 1177.55
   178.4 1178.88   188.4  1180.7   198.3 1184.24   208.2 1188.44   218.1 1192.88
     228 1197.69   247.8 1208.19   267.7 1217.38   277.6 1220.89   287.5 1222.89
   297.4 1223.77   327.1 1230.32   337.1 1232.46     347 1234.43
#Mann= 3 , 0 , 0
       0      .1       0   151.1    .045       0   166.1      .1       0
Bank Sta=151.1,166.1
XS Rating Curve= 0 ,0
Exp/Cntr=0.3,0.1

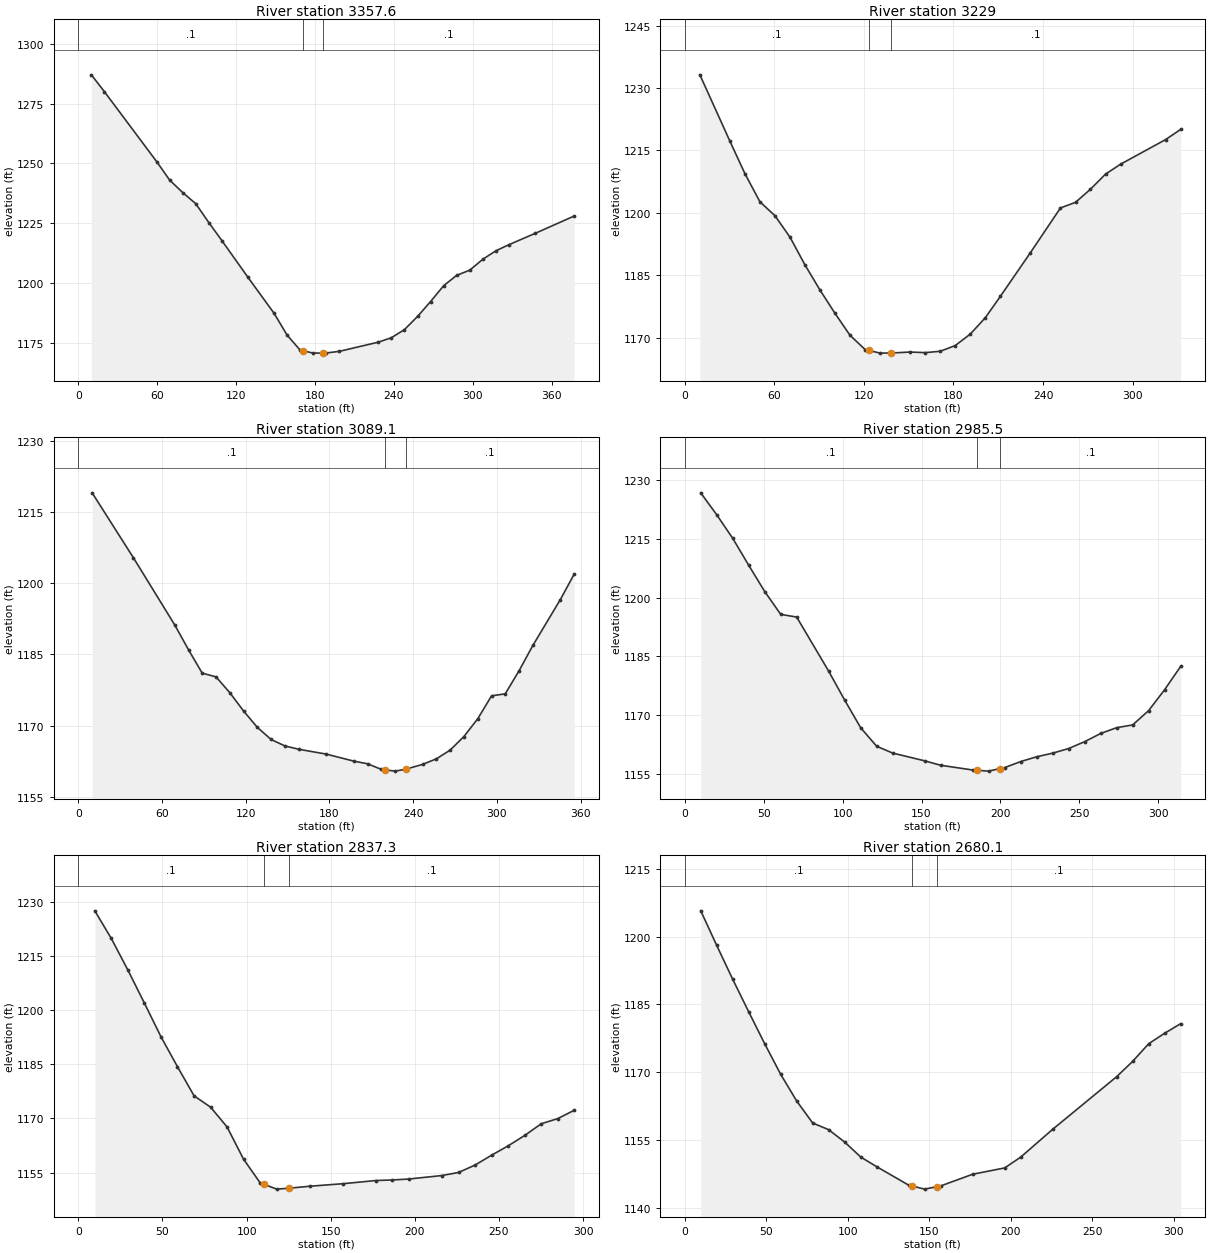
Type RM Length L Ch R = 1 ,3357.6  ,129.8,128.6,127.5
XS GIS Cut Line= 2
     1659842.281      230492.142     1659716.345      230847.658
#Sta/Elev= 30
     9.9 1287.04    19.9 1279.96    59.6 1250.77    69.5 1243.04    79.4 1237.85
    89.3 1233.21    99.3 1225.29   109.2 1217.77     129 1202.46   148.9 1187.41
   158.8 1178.29   168.7 1172.03   171.2 1171.71   178.7 1170.75   186.2  1170.8
   188.6 1170.81   198.5 1171.49   228.3 1175.34   238.2  1177.2   248.1 1180.58
   258.1  1186.1     268 1192.32   277.9 1198.91   287.8 1203.24   297.8 1205.42
   307.7 1209.97   317.6 1213.49   327.5 1216.05   347.4 1220.76   377.2 1228.04
#Mann= 3 , 0 , 0
       0      .1       0   171.2    .045       0   186.2      .1       0
Bank Sta=171.2,186.2
XS Rating Curve= 0 ,0
Exp/Cntr=0.3,0.1

Type RM Length L Ch R = 1 ,3229    ,142,139.9,137.8
XS GIS Cut Line= 2
     1659696.167      230496.581     1659622.499      230820.551
#Sta/Elev= 29
    10.1 1233.17    30.2 1217.24    40.3 1209.41    50.3 1202.68    60.4 1199.31
    70.5 1194.15    80.5  1187.5    90.6 1181.44   100.7 1175.82   110.7 1170.57
   120.8 1167.16   123.4 1166.93   130.9 1166.29   138.4 1166.32     151 1166.55
   161.1 1166.41   171.2 1166.74   181.2 1168.11   191.3 1170.87   201.4 1174.83
   211.4 1179.92   231.6 1190.45   251.7 1201.18   261.8 1202.53   271.8 1205.68
   281.9 1209.31     292  1211.7   322.2 1217.62   332.2 1220.05
#Mann= 3 , 0 , 0
       0      .1       0   123.4    .045       0   138.4      .1       0
Bank Sta=123.4,138.4
XS Rating Curve= 0 ,0
Exp/Cntr=0.3,0.1

Type RM Length L Ch R = 1 ,3089.1  ,101.6,103.6,105.7
XS GIS Cut Line= 2
     1659573.693      230443.105      1659505.71      230791.935
#Sta/Elev= 30
     9.9 1219.07    39.5 1205.37    69.1 1191.21      79 1185.96    88.8 1181.04
    98.7 1180.26   108.6 1176.91   118.5 1173.04   128.3 1169.61   138.2 1167.05
   148.1 1165.69     158 1164.99   177.7 1163.97   197.4 1162.49   207.3 1161.93
   217.2 1160.75   219.6 1160.66   227.1 1160.38   234.6 1160.78   246.8  1161.8
   256.7 1162.98   266.5 1164.81   276.4 1167.68   286.3 1171.43   296.2 1176.26
     306 1176.68   315.9 1181.54   325.8 1186.89   345.5 1196.56   355.4 1201.92
#Mann= 3 , 0 , 0
       0      .1       0   219.6    .045       0   234.6      .1       0
Bank Sta=219.6,234.6
XS Rating Curve= 0 ,0
Exp/Cntr=0.3,0.1

Type RM Length L Ch R = 1 ,2985.5  ,146,148.1,150.2
XS GIS Cut Line= 2
     1659482.698       230464.77     1659393.962      230766.138
#Sta/Elev= 30
    10.1 1226.76    20.3 1221.11    30.4 1215.11    40.5 1208.25    50.7  1201.5
    60.8 1195.69    70.9 1195.01    91.2 1181.16   101.3 1173.79   111.5 1166.69
   121.6 1161.98   131.7 1160.25     152 1158.26   162.1 1157.13   182.4 1155.92
     185 1155.85   192.5 1155.63     200  1156.3   202.7 1156.53   212.8 1158.07
     223  1159.3   233.1 1160.22   243.2  1161.4   253.4 1163.16   263.5 1165.25
   273.6 1166.73   283.8 1167.44   293.9 1171.09     304 1176.41   314.2 1182.38
#Mann= 3 , 0 , 0
       0      .1       0     185    .045       0     200      .1       0
Bank Sta=185,200
XS Rating Curve= 0 ,0
Exp/Cntr=0.3,0.1

Type RM Length L Ch R = 1 ,2837.3  ,166,157.2,148.4
XS GIS Cut Line= 2
     1659361.314      230444.678     1659254.161      230719.258
#Sta/Elev= 28
     9.8 1227.55    19.6 1219.88    29.5 1211.09    39.3 1201.95    49.1 1192.66
    58.9 1184.36    68.8 1176.27    78.6 1173.13    88.4 1167.65    98.2 1158.71
   108.1 1152.14   110.4 1151.73   117.9 1150.41   125.4 1150.67   137.5 1151.21
   157.2 1151.91   176.8 1152.79   186.7 1152.95   196.5 1153.21   216.1 1154.18
     226 1155.03   235.8 1157.08   245.6 1159.81   255.4 1162.39   265.3 1165.28
   275.1 1168.52   284.9 1169.95   294.7 1172.26
#Mann= 3 , 0 , 0
       0      .1       0   110.4    .045       0   125.4      .1       0
Bank Sta=110.4,125.4
XS Rating Curve= 0 ,0
Exp/Cntr=0.3,0.1

Type RM Length L Ch R = 1 ,2680.1  ,242.8,244.7,246.6
XS GIS Cut Line= 2
     1659162.454      230409.671     1659166.911      230713.922
#Sta/Elev= 26
     9.8 1205.72    19.6 1198.06    29.4 1190.57    39.3 1183.31    49.1 1176.25
    58.9 1169.49    68.7  1163.6    78.5 1158.74    88.3 1157.27    98.2  1154.5
     108 1151.21   117.8 1149.07   137.4 1144.99   139.7 1144.78   147.2 1144.11
   154.7 1144.65     157 1144.81   176.7 1147.41   196.3  1148.8   206.1 1151.18
   225.8 1157.36     265 1168.99   274.8 1172.37   284.7  1176.3   294.5 1178.62
   304.3 1180.73
#Mann= 3 , 0 , 0
       0      .1       0   139.7    .045       0   154.7      .1       0
Bank Sta=139.7,154.7
XS Rating Curve= 0 ,0
Exp/Cntr=0.3,0.1

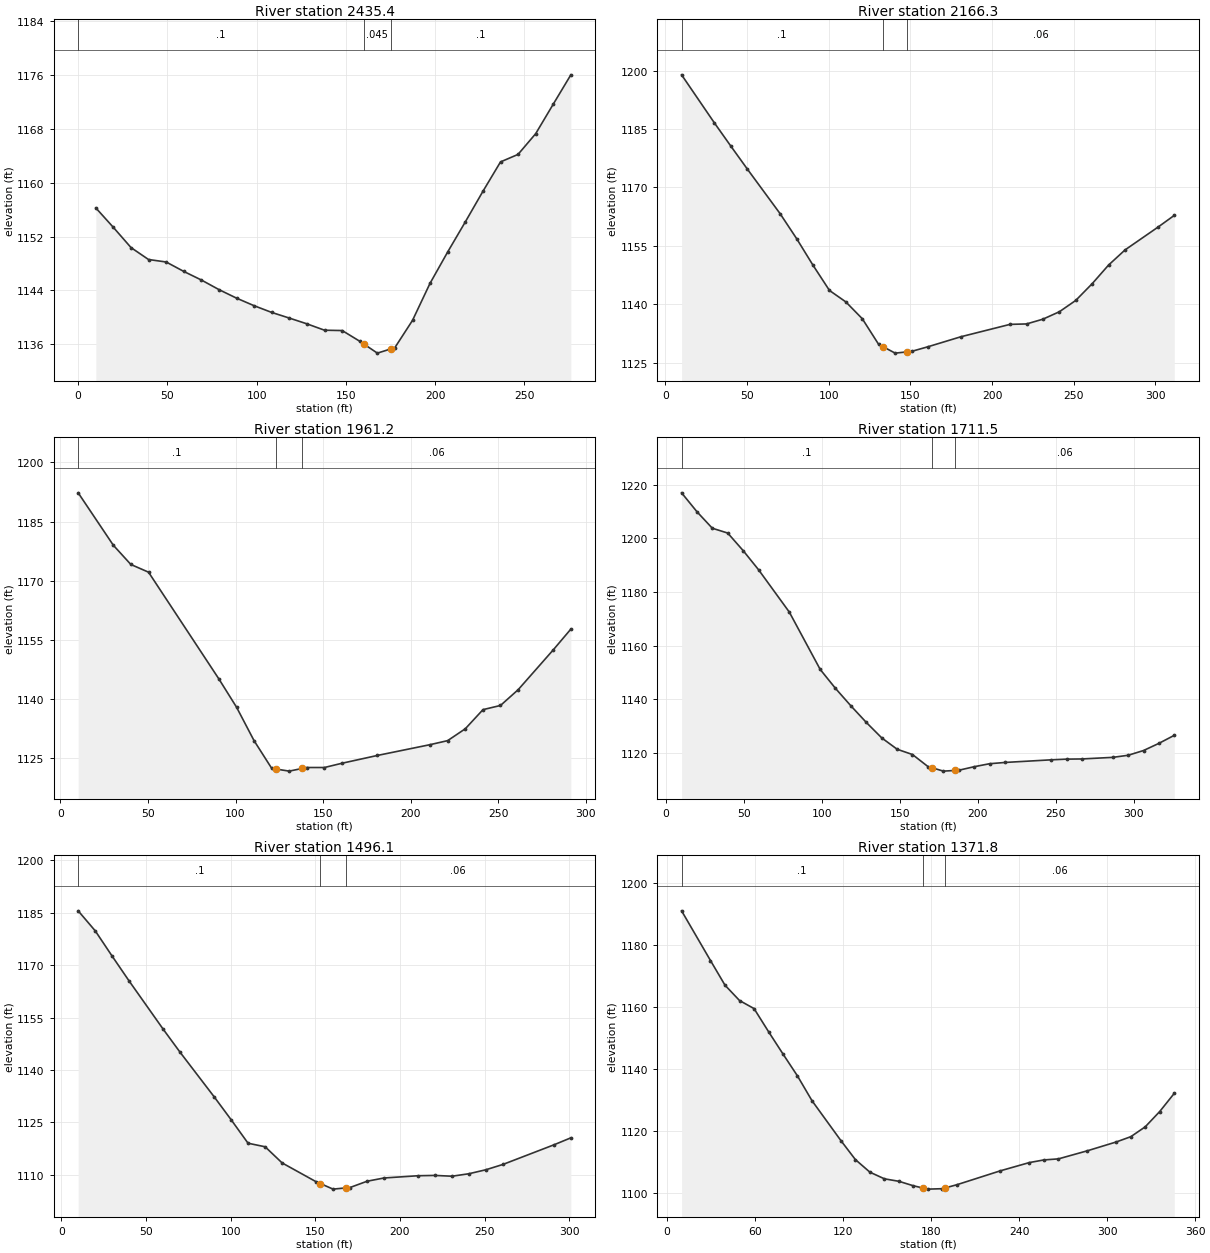
Type RM Length L Ch R = 1 ,2435.4  ,260.5,269.1,277.6
XS GIS Cut Line= 2
     1658942.903      230435.304     1658922.842      230710.578
#Sta/Elev= 30
     9.9 1156.24    19.7 1153.36    29.6 1150.36    39.4 1148.59    49.3 1148.22
    59.1 1146.83      69 1145.55    78.9 1144.12    88.7 1142.86    98.6 1141.73
   108.4 1140.74   118.3  1139.9   128.1 1139.05     138  1138.1   147.9 1138.05
   157.7 1136.47   160.1 1136.04   167.6  1134.7   175.1 1135.32   177.4 1135.51
   187.3 1139.56   197.1 1145.05     207 1149.71   216.9 1154.18   226.7 1158.69
   236.6 1163.07   246.4 1164.18   256.3 1167.26   266.1 1171.62     276 1175.99
#Mann= 3 , 0 , 0
       0      .1       0   160.1    .045       0   175.1      .1       0
Bank Sta=160.1,175.1
XS Rating Curve= 0 ,0
Exp/Cntr=0.3,0.1

Type RM Length L Ch R = 1 ,2166.3  ,211.2,205.1,198.9
XS GIS Cut Line= 2
     1658777.961      230351.719      1658643.11      230632.565
#Sta/Elev= 27
      10 1198.89    30.1 1186.54    40.2 1180.56    50.2 1174.73    70.3 1163.26
    80.4 1156.86    90.4 1150.05   100.5 1143.56   110.5 1140.63   120.6  1136.3
   130.6 1129.72   133.2 1129.14   140.7 1127.48   148.2 1127.81   150.7 1127.92
   160.8 1129.12   180.9 1131.68     211 1134.86   221.1 1134.97   231.1 1136.19
   241.2  1138.1   251.2    1141   261.3 1145.31   271.3 1150.08   281.4 1153.97
   301.5  1159.8   311.5 1162.82
#Mann= 3 , 0 , 0
      10      .1       0   133.2    .045       0   148.2     .06       0
Bank Sta=133.2,148.2
XS Rating Curve= 0 ,0
Exp/Cntr=0.3,0.1

Type RM Length L Ch R = 1 ,1961.2  ,240.9,249.7,258.4
XS GIS Cut Line= 2
     1658551.806      230282.275     1658500.741      230569.411
#Sta/Elev= 23
    10.1 1192.29    30.2 1178.96    40.2 1174.08    50.3 1172.12    90.5 1144.98
   100.6 1137.79   110.6 1129.29   120.7 1122.24   123.2 1122.07   130.7 1121.55
   138.2 1122.24   140.8 1122.47   150.8 1122.47   160.9 1123.56     181 1125.53
   211.2 1128.28   221.2  1129.3   231.3 1132.32   241.4 1137.18   251.4 1138.24
   261.5 1142.25   281.6  1152.4   291.6 1157.65
#Mann= 3 , 0 , 0
    10.1      .1       0   123.2    .045       0   138.2     .06       0
Bank Sta=123.2,138.2
XS Rating Curve= 0 ,0
Exp/Cntr=0.3,0.1

Type RM Length L Ch R = 1 ,1711.5  ,219.8,215.4,211
XS GIS Cut Line= 2
     1658392.802      230175.869     1658220.059      230452.258
#Sta/Elev= 30
     9.9 1217.05    19.8 1209.96    29.6 1203.83    39.5 1202.02    49.4 1195.46
    59.3  1188.3      79  1172.5    98.8 1151.09   108.6 1144.01   118.5 1137.48
   128.4 1131.28   138.3  1125.5   148.2 1121.26     158  1119.3   167.9 1114.81
   170.3  1114.4   177.8  1113.1   185.3 1113.35   187.7 1113.43   197.5 1114.74
   207.4 1115.86   217.3 1116.34   246.9 1117.32   256.8 1117.58   266.7 1117.65
   286.4 1118.24   296.3 1119.02   306.2  1120.8   316.1 1123.49   325.9 1126.47
#Mann= 3 , 0 , 0
     9.9      .1       0   170.3    .045       0   185.3     .06       0
Bank Sta=170.3,185.3
XS Rating Curve= 0 ,0
Exp/Cntr=0.3,0.1

Type RM Length L Ch R = 1 ,1496.1  ,123.8,124.3,124.8
XS GIS Cut Line= 2
     1658168.346      230074.216     1658060.242      230355.062
#Sta/Elev= 26
      10 1185.52    20.1 1179.78    30.1 1172.53    40.1 1165.44    60.2 1151.66
    70.2 1145.05    90.3 1132.32   100.3 1125.78   110.3 1119.05   120.4 1118.03
   130.4 1113.42   150.5 1108.03     153 1107.51   160.5 1105.92     168 1106.27
   170.5 1106.38   180.6 1108.18   190.6 1109.11   210.7 1109.75   220.7 1109.84
   230.7 1109.61   240.7 1110.32   250.8 1111.47   260.8 1112.98   290.9 1118.59
   300.9 1120.59
#Mann= 3 , 0 , 0
      10      .1       0     153    .045       0     168     .06       0
Bank Sta=153,168
XS Rating Curve= 0 ,0
Exp/Cntr=0.3,0.1

Type RM Length L Ch R = 1 ,1371.8  ,272.5,267.4,262.3
XS GIS Cut Line= 2
     1658058.944        230023.6     1657928.351      230343.804
#Sta/Elev= 30
     9.9 1190.99    29.6 1174.97    39.5 1167.02    49.4 1162.08    59.3 1159.48
    69.2 1152.03      79 1144.87    88.9 1137.78    98.8  1129.8   118.6 1116.88
   128.4 1110.81   138.3 1106.75   148.2 1104.61   158.1 1103.81     168 1102.36
   174.31101.673   177.8 1101.29   187.7 1101.43   189.31101.637   197.6 1102.71
   227.2 1107.19     247 1109.85   256.9  1110.7   266.8 1111.04   286.5 1113.64
   306.3  1116.5   316.2  1118.2     326 1121.37   335.9 1126.31   345.8 1132.16
#Mann= 3 , 0 , 0
     9.9      .1       0   174.3    .045       0   189.3     .06       0
Bank Sta=174.3,189.3
XS Rating Curve= 0 ,0
Exp/Cntr=0.3,0.1

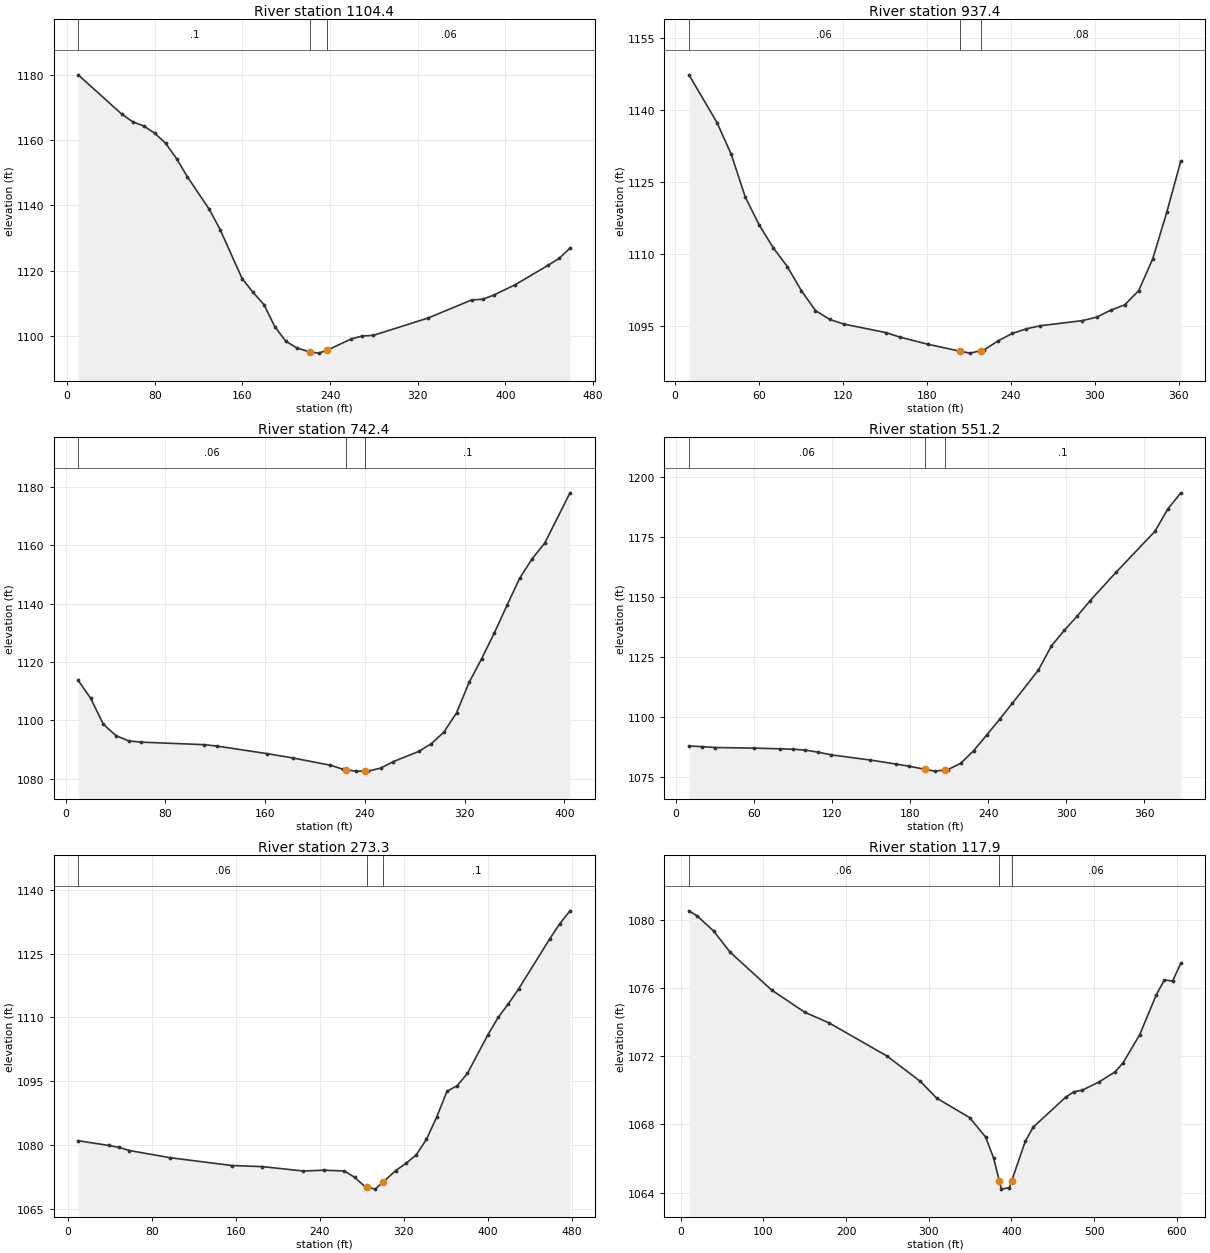
Type RM Length L Ch R = 1 ,1104.4  ,155.5,167.1,178.6
XS GIS Cut Line= 2
     1657780.366      229872.655     1657707.321      230325.838
#Sta/Elev= 30
      10 1180.15    49.9 1168.06    59.9  1165.7    69.9 1164.45    79.8 1162.24
    89.8 1159.15    99.8 1154.44   109.8 1148.78   129.7 1138.84   139.7 1132.55
   159.7 1117.54   169.6 1113.36   179.6 1109.56   189.6 1102.74   199.6 1098.28
   209.6 1096.25     222 1094.95   229.5 1094.64     237 1095.48   259.5 1099.03
   269.4  1099.9   279.4 1100.09   329.3 1105.41   369.2 1110.98   379.2 1111.19
   389.2 1112.44   409.1 1115.68   439.1 1121.65   449.1 1123.76     459 1126.89
#Mann= 3 , 0 , 0
      10      .1       0     222    .045       0     237     .06       0
Bank Sta=222,237
XS Rating Curve= 0 ,0
Exp/Cntr=0.3,0.1

Type RM Length L Ch R = 1 ,937.4   ,191.7,195,198.3
XS GIS Cut Line= 2
     1657734.345      229871.661     1657509.575      230154.821
#Sta/Elev= 30
      10 1147.39    30.1 1137.38    40.2 1130.79    50.2  1121.9    60.3 1115.97
    70.3 1111.24    80.3 1107.34    90.4 1102.28   100.4 1098.16   110.5 1096.31
   120.5 1095.34   150.6 1093.56   160.7 1092.61   180.8 1091.11   203.4 1089.68
   210.9 1089.26   218.4 1089.76   220.9 1089.92     231 1091.84     241 1093.37
   251.1 1094.34   261.1 1094.98   291.2 1096.05   301.3 1096.78   311.3 1098.22
   321.4 1099.34   331.4 1102.32   341.4 1108.94   351.5 1118.72   361.5  1129.4
#Mann= 3 , 0 , 0
      10     .06       0   203.4    .045       0   218.4     .08       0
Bank Sta=203.4,218.4
XS Rating Curve= 0 ,0
Exp/Cntr=0.3,0.1

Type RM Length L Ch R = 1 ,742.4   ,188.5,191.2,193.9
XS GIS Cut Line= 2
     1657633.464      229742.042     1657339.179      230019.607
#Sta/Elev= 30
    10.1 1113.71    20.2 1107.54    30.3 1098.69    40.5 1094.76    50.6    1093
    60.7 1092.56   111.2 1091.69   121.4 1091.21   161.8 1088.61     182 1087.16
   212.4 1084.65   222.5 1083.26   225.1  1083.1   232.6 1082.63   240.1 1082.64
   242.7 1082.64   252.8 1083.69   262.9  1085.9   283.2 1089.38   293.3 1092.01
   303.4 1096.01   313.5 1102.56   323.6    1113   333.7 1121.16   343.9 1130.01
     354  1139.4   364.1 1148.63   374.2 1155.37   384.3 1160.74   404.5 1177.91
#Mann= 3 , 0 , 0
    10.1     .06       0   225.1    .045       0   240.1      .1       0
Bank Sta=225.1,240.1
XS Rating Curve= 0 ,0
Exp/Cntr=0.3,0.1

Type RM Length L Ch R = 1 ,551.2   ,282.3,277.8,273.4
XS GIS Cut Line= 2
     1657542.013      229612.825     1657229.961       229843.52
#Sta/Elev= 30
      10 1087.94    19.9 1087.69    29.9 1087.32    59.7 1087.06    79.6 1086.78
    89.6 1086.61    99.5 1086.24   109.5 1085.35   119.4 1084.25   149.3 1082.11
   169.2 1080.42   179.1 1079.53   191.5 1078.21     199 1077.47   206.5 1077.92
     209 1078.06   218.9 1080.75   228.9 1086.03   238.8 1092.47   248.8 1099.09
   258.7 1105.81   278.6 1119.62   288.6 1129.63   298.5 1136.16   308.5 1142.13
   318.4 1148.55   338.3 1160.36   368.2 1177.46   378.1 1186.75   388.1  1193.5
#Mann= 3 , 0 , 0
      10     .06       0   191.5    .045       0   206.5      .1       0
Bank Sta=191.5,206.5
XS Rating Curve= 0 ,0
Exp/Cntr=0.3,0.1

Type RM Length L Ch R = 1 ,273.3   ,149.3,155.4,161.5
XS GIS Cut Line= 3
     1657485.175      229512.522     1657267.853      229456.799
     1657097.339      229645.144
#Sta/Elev= 30
     9.8  1081.1      39 1079.98    48.8 1079.53    58.5  1078.8    97.5 1077.11
   156.1 1075.28   185.3 1075.02   224.4 1073.99   243.9 1074.18   263.4    1074
   273.2 1072.51     283 1070.35   285.3 1070.21   292.8 1069.74   300.3 1071.38
   312.3 1074.09   322.1 1075.78   331.8 1077.74   341.6  1081.4   351.4 1086.65
   361.2 1092.68   370.9 1094.01   380.7 1096.89   400.2 1105.95     410 1110.03
   419.8 1113.25   429.6 1116.76   458.9 1128.37   468.6 1131.99   478.4 1135.02
#Mann= 3 , 0 , 0
     9.8     .06       0   285.3    .045       0   300.3      .1       0
Bank Sta=285.3,300.3
XS Rating Curve= 0 ,0
Exp/Cntr=0.3,0.1

Type RM Length L Ch R = 1 ,117.9   ,134.3,117.9,101.6
XS GIS Cut Line= 4
     1657481.832      229494.691     1657156.527      229366.752
     1657075.299      229418.314     1656999.266      229558.216
#Sta/Elev= 30
      10 1080.53      20 1080.23    39.9 1079.34    59.9  1078.1   109.9 1075.89
   149.8 1074.59   179.8 1073.95   249.7 1072.01   289.6 1070.54   309.6 1069.55
   349.6  1068.4   368.8 1067.27   378.4 1066.05   385.5 1064.69     388 1064.21
   397.7  1064.3   400.51064.711   416.9 1067.02   426.5 1067.85   465.7  1069.6
   475.6 1069.92   485.6 1070.01   505.5 1070.48   525.4 1071.08   535.3 1071.63
   555.2 1073.26   575.1 1075.58   585.1 1076.48     595 1076.41     605 1077.46
#Mann= 3 , 0 , 0
      10     .06       0   385.5    .045       0   400.5     .06       0
Bank Sta=385.5,400.5
XS Rating Curve= 0 ,0
Exp/Cntr=0.3,0.1

Chan Stop Cuts=-1
Use User Specified Reach Order=0